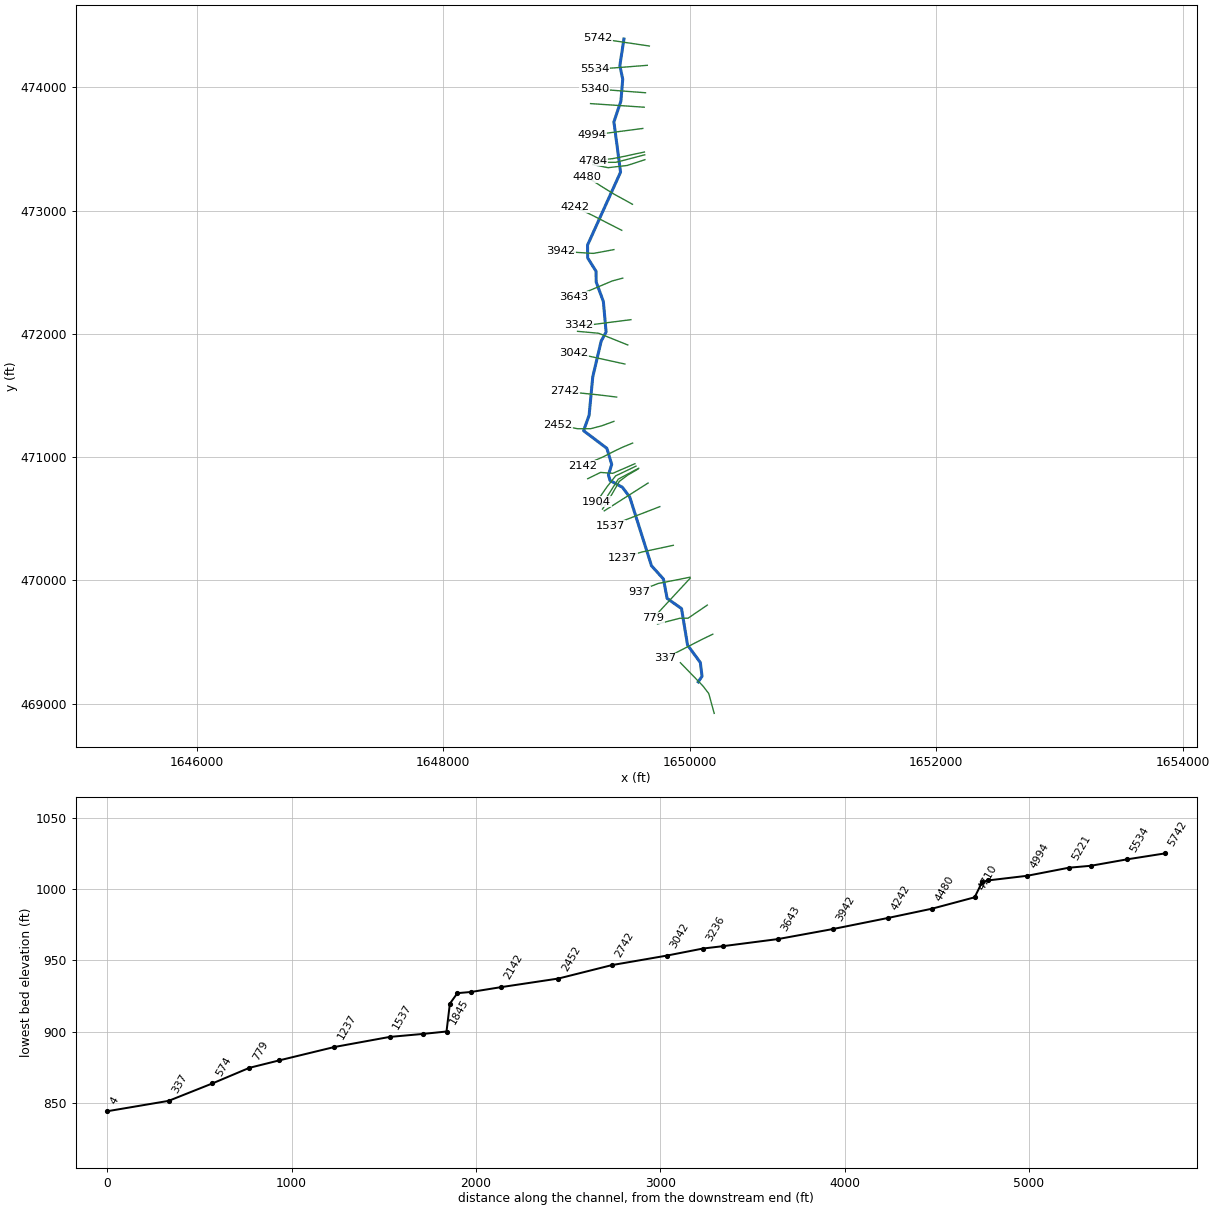
--- MagtyRnT1.prj (project) ---

Proj Title=MagtyRnT1
Current Plan=p01
Default Exp/Contr=0,0
English Units
Geom File=g01
Flow File=f01
Plan File=p01
BEGIN DESCRIPTION:
---------- MODELED AS PART OF WVEM CTP PROGRAM, 2025----------
Stream Name: Maggoty Run Tributary 1
Flood Zone: AFH
Marshall County, WV
HEC-RAS Version: RAS 6.6
Vertical Datum: NAVD88
Projection: NAD 1983 StatePlane West Virginia N FIPS 4701 (US Feet)
Terrain: 1-meter West Virginia FEMA R3 South Central (collected 2018-2019)
Land Use: 2024 NLCD
Hydrologic Method:
Duda et al., "Estimation of magnitude and frequency of floods for rural, unregulated streams in and near Virginia and West Virginia." September 8, 2025.
Additional Model Notes:
None
END DESCRIPTION:
DSS Export Rating Curves= 0
DSS Export Rating Curve Sorted= 0
DSS Export Volume Flow Curves= 0
DXF OffsetX= 0
DXF OffsetY= 0
DXF ScaleX= 0
DXF ScaleY= 0

--- MagtyRnT1.p01 (plan) ---

Plan Title=Floodplain
Program Version=6.60
Short Identifier=Floodplain
Geom File=g01
Flow File=f01
Subcritical Flow
K Sum by GR= 0
Std Step Tol= 0.01
Critical Tol= 0.01
Num of Std Step Trials= 20
Max Error Tol= 0.3
Flow Tol Ratio= 0.001
Split Flow NTrial= 30
Split Flow Tol= 0.02
Split Flow Ratio= 0.02
Log Output Level= 0
Friction Slope Method= 1
Unsteady Friction Slope Method= 2
Unsteady Bridges Friction Slope Method= 1
Parabolic Critical Depth
Global Vel Dist= 0 , 0 , 0
Global Log Level= 0
CheckData=False
Encroach Param=-1 ,0,0, 0
Flow Ratio Tolerance=0.1
Flow Ratio Min Ratio=0.5
Flow Ratio Max Ratio=4
Flow Ratio Max Iterations= 10
Mapping Interval=1HOUR
Computation Time Step Use Courant=        0
Computation Time Step Use Time Series=    0
Computation Time Step Count To Double=0
Computation Time Step Max Doubling=0
Computation Time Step Max Halving=0
Computation Time Step Residence Courant=0
Run HTab= 0
Run UNet= 0
Run Sediment= 0
Run PostProcess= 0
Run WQNet= 0
Run RASMapper=-1
UNET Theta= 0
UNET Theta Warmup= 0
UNET ZTol= 0
UNET ZSATol= 0
UNET MxIter= 0
UNET Max Iter WO Improvement= 0
UNET MaxInSteps= 0
UNET DtIC= 0
UNET DtMin= 0
UNET MaxCRTS= 0
UNET WFStab= 0
UNET SFStab= 0
UNET WFX= 1
UNET SFX= 1
UNET Gravity=32.17405
UNET 1D Methodology=Finite Difference
UNET DSS MLevel= 1
UNET Pardiso=0
UNET DZMax Abort= 0
UNET Use Existing IB Tables= 0
UNET Froude Reduction=False
UNET Froude Limit= 0
UNET Froude Power= 0
UNET D1 Cores= 0
UNET WindReference=Eulerian
UNET WindDragFormulation=Hsu (1988)
UNET D2 Coriolis=0
UNET D2 Cores= 0
UNET D2 Theta= 1
UNET D2 Theta Warmup= 1
UNET D2 Z Tol= 0.01
UNET D2 Volume Tol= 0.01
UNET D2 Max Iterations= 20
UNET D2 Advanced Convergence=0
UNET D2 WS Max Tol=0.15
UNET D2 WS RMS Tol=0.002
UNET D2 WS Stall Tol=1
UNET D2 Equation= 0
UNET D2 RampUpFraction=0.1
UNET D2 TimeSlices= 1
UNET D2 Turbulence Formulation=Non-Conservative (original)
UNET D2 Eddy Viscosity=0.3
UNET D2 Transverse Eddy Viscosity=0.1
UNET D2 Smagorinsky Mixing=0
UNET D2 BCVolumeCheck=0
UNET D2 Cores=0
UNET D2 SolverType=PARDISO (Direct)
UNET D2 Minimum Iterations= 3
UNET D2 Maximum Iterations= 30
UNET D2 Restart Number= 10
UNET D2 Relaxation Coeff=1.3
UNET D2 SOR Precondition Iterations= 10
UNET D2 ILUT Maximum Fill= 8
UNET D2 ILUT Tolerance=1E-08
UNET D2 Convergence Tolerance=0.00001
PS Theta= 1
PS WS Tol= 0.01
PS Volume Tol= 0.01
PS Max Iterations= 20
PS Equation= 0
PS Advance Time Step=-1
PS Target Courant=0.9
PS Time Slices= 1
PS Iterate With 2D=0
PS Project Initial WSE from DS=-1
PS Ramp Up Initial WSE from US=-1
PS Cores=0
UNET D1D2 MaxIter= 0
UNET D1D2 ZTol=0.01
UNET D1D2 QTol=0.1
UNET D1D2 MinQTol=1
Write IC File= 0
Write IC File at Fixed DateTime=0
Write IC File at Sim End=0
Echo Input=False
Echo Parameters=False
Echo Output=False
Write Detailed= 0
HDF Write Warmup=0
HDF Write Time Slices=0
HDF Flush=0
HDF Compression= 1
HDF Chunk Size= 1
HDF Spatial Parts= 1
HDF Use Max Rows=0
HDF Fixed Rows= 1
Calibration Method= 0
Calibration Iterations= 20
Calibration Max Change=0.05
Calibration Tolerance=0.2
Calibration Maximum=1.5
Calibration Minimum=0.5
Calibration Optimization Method= 1
WQ AD Non Conservative
WQ ULTIMATE=-1
WQ Max Comp Step=1HOUR
WQ Output Interval=15MIN
WQ Output Selected Increments= 0
WQ Create Restart=0
WQ Fixed Restart=0
WQ System Summary=0
WQ Write To DSS=0
Sorting and Armoring Iterations= 10
XS Update Threshold= 0.02
Bed Roughness Predictor= 0
Processes Affected by Predictor=Sediment Only
Hydraulics Update Threshold= 0.02
Energy Slope Method= 1
Volume Change Method= 1
Sediment Retention Method= 0
Sediment TS Multiplier= 1
Warm Up Method= 0
XS Weighting Method= 0
Number of US Weighted Cross Sections= 1
Number of DS Weighted Cross Sections= 1
Upstream XS Weight=0
Main XS Weight=1
Downstream XS Weight=0
Number of DS XS's Weighted with US Boundary= 1
Upstream Boundary Weight= 1
Weight of XSs Associated with US Boundary= 0
Number of US XS's Weighted with DS Boundary= 1
Downstream Boundary Weight= 0.5
Weight of XSs Associated with DS Boundary= 0.5
Percentile Method= 0
Sediment Output Level= 3
Mass or Volume Output= 0
Output Increment Type= 1
Profile and TS Output Increment= 1
Transport Output Increment 1
XS Output Flag= 0
XS Output Increment= 10
Read HDF5 Sediment Hotstart= 0
Sediment Hotstart Type= 0
Write Gradation File= 0
Read Gradation Hotstart= 0
Write HDF5 File= 1
Write Binary Output= 1
Write DSS Sediment File= 0
DSS Sediment Output Type= 1
SV Curve= 0
Specific Gage Flag= 0
Subcell Erosion Methods= 0
Subcell Deposition Methods= 0
Advection Scheme= 1
Matrix Solver= 0
Implicit Weighting Factor= 1
Maximum Outer Loop Convergence Iterations= 5
Convergence Maximum Absolute= 0.001
Convergence RMSE= 0.0001
Grain Fractions Max Abs Error= 0.001
Max Subgrid Regions= 1
Max Subgrid Length Scale= 3.402823E+38
Initial Layer Thickness= 3
Min Layer Thickness= 0.1
Max Layer Thickness= 6
Number of Layers= 5

--- MagtyRnT1.f01 (steady flow) ---

Flow Title=Flow
Program Version=6.60
Number of Profiles= 1
Profile Names=P100yr
River Rch & RM=MagtyRnT1,Main            ,5742
     784
River Rch & RM=MagtyRnT1,Main            ,3942
     876
River Rch & RM=MagtyRnT1,Main            ,4
    2490
Boundary for River Rch & Prof#=MagtyRnT1,Main            , 1
Up Type= 0
Dn Type= 1
Dn Known WS=848.9
DSS Import GetInterval= 0
DSS Import GetPeak= 0
DSS Import FillOption= 0

--- MagtyRnT1.g01 (geometry) ---

Geom Title=Geometry
Program Version=6.60

River Reach=MagtyRnT1       ,Main
Reach XY= 30
1649467.43200001474392.754000023      1649434.41474176.973000005
1649457.75300002474067.0890000021649442.95000002473889.453999996
     1649386.189473720.7539999931649440.10300002473312.708000019
1649172.51199999472721.7290000171649173.08100002472617.539000005
     1649241.402472508.2250000091649242.54099999472421.116000012
1649300.61399999 472263.40700002     1649322.818472016.312000006
1649282.96400002471942.2979999931649214.64300002471652.502000004
     1649185.037471339.932000011     1649140.059471215.245000005
1649329.08100002471072.340000018     1649368.366470941.391000003
1649341.60699999470857.1280000061649354.70100002470811.580000013
1649454.53835981470756.6357439161649514.46412638470677.693122879
1649691.00600001470119.7559999971649787.97200002470012.114999995
1649817.87360417469854.9201958841649934.75600001469771.922999993
1649983.82700002469475.900000021     1650087.402469334.361000016
     1650101.248469222.8599999991650070.25569336469177.409178644

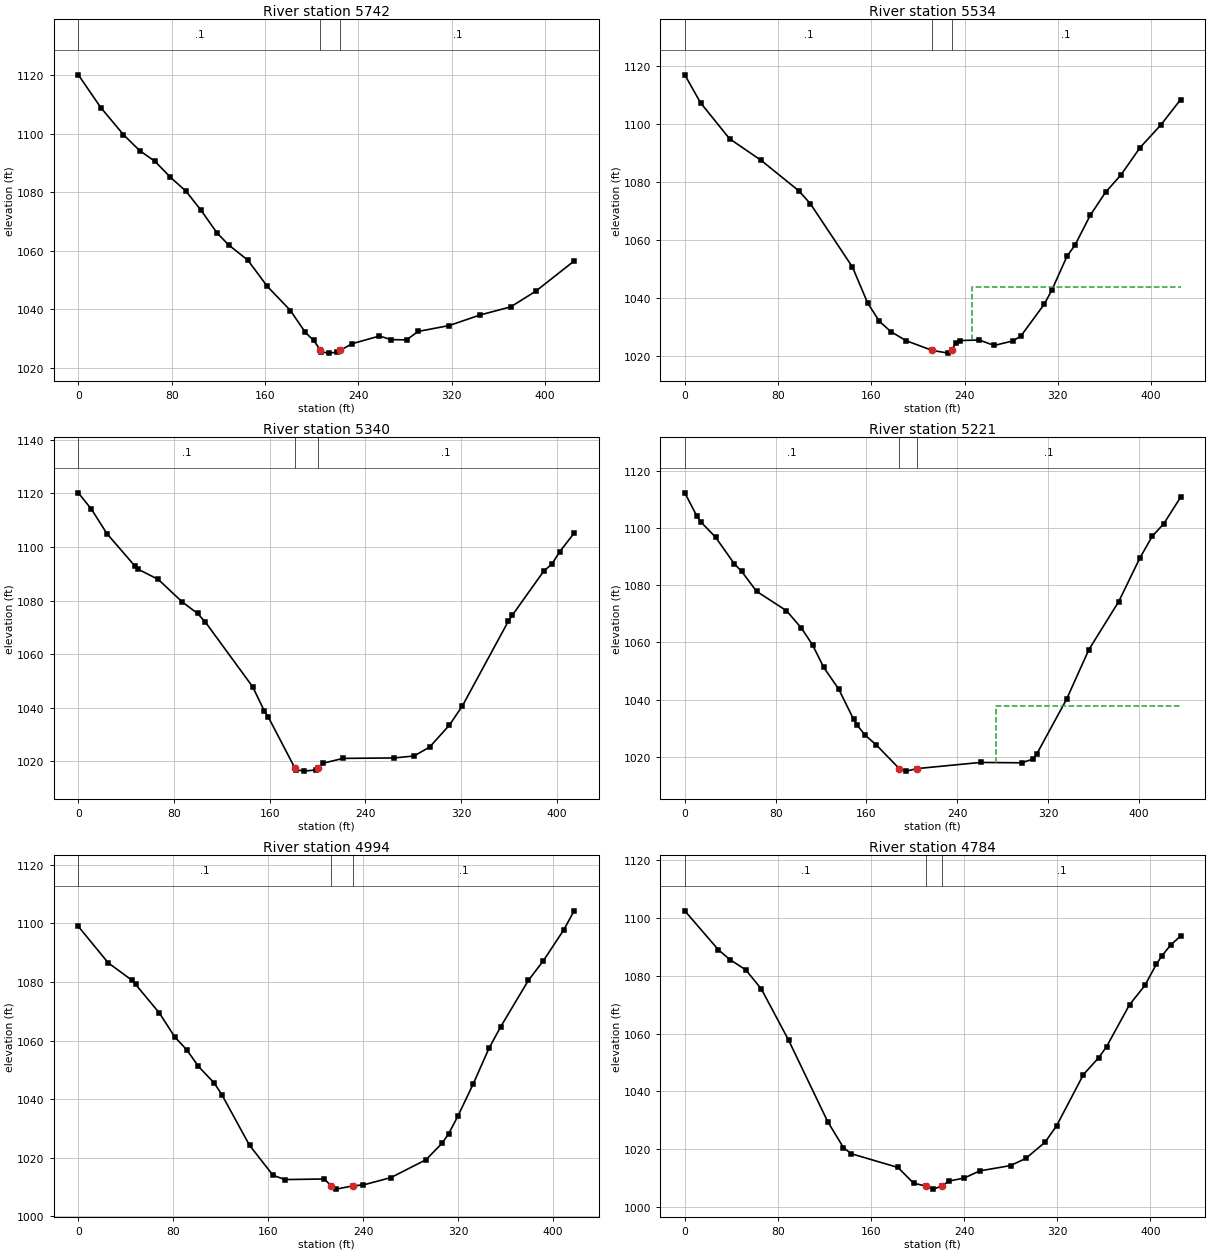
Type RM Length L Ch R = 1 ,5742    ,205.8,207.8,209.4
XS GIS Cut Line= 6
1649673.84487717474336.0755757541649587.29419726474348.929224595
1649513.10766584474359.9469190841649414.19250934474374.637178421
1649340.00630601474385.6545448451649253.45562609474398.508849844
#Sta/Elev= 30
       0 1120.16    19.3 1108.94    38.6 1099.74    52.5 1094.27    65.7 1090.59
      79 1085.13    92.3 1080.37   105.1 1073.91   118.8 1066.17   128.8 1062.03
   145.3 1056.81   161.9  1047.9   181.8  1039.6   194.6  1032.1   201.7 1029.38
  207.561026.057   208.4 1025.45   214.8 1025.04   221.6 1025.36   224.71026.055
   234.9 1028.29   258.1 1030.88   268.1 1029.66   281.3 1029.57   291.3 1032.45
   317.8 1034.46   344.3 1038.07   370.7 1040.86   392.2 1046.24     425 1056.54
#Mann= 3 ,-1,0
       0      .1       0  207.56    .045       0   224.7      .1       0
Bank Sta=207.56,224.7
XS Rating Curve= 0 ,0
Exp/Cntr(USF)=0,0
Exp/Cntr=0.3,0.1

Type RM Length L Ch R = 1 ,5534    ,195.3,193.9,192.5
XS GIS Cut Line= 6
1649656.99443573474179.6223970741649569.76035824474172.807121986
1649494.98819806474166.9652701571649395.29187516474159.176571826
 1649320.4426154474154.3252035631649232.94147807474147.492211993
#Sta/Elev= 30
       0 1116.86    13.5 1107.22    38.4 1094.81    65.4 1087.36    97.7 1076.87
   107.6 1072.44   143.8 1050.53   156.9 1038.07   166.8 1031.85   176.7 1028.25
   189.8 1025.12  212.121021.765     226 1020.82  228.971021.765   232.6 1024.46
   235.9 1025.16   252.4 1025.35   265.5 1023.47   281.9 1025.09   288.5 1026.83
   308.3 1037.69   314.8 1042.54     328 1054.39   334.6    1058   347.7 1068.35
   360.9 1076.34     374 1082.26   390.5 1091.74   408.2 1099.51   425.3 1108.32
#Mann= 3 ,-1,0
       0      .1       0  212.12    .045       0  228.97      .1       0
#XS Ineff= 2 , 0
                          246.18         1043.73
Permanent Ineff=
       F       F
Bank Sta=212.12,228.97
XS Rating Curve= 0 ,0
Exp/Cntr(USF)=0,0
Exp/Cntr=0.3,0.1

Type RM Length L Ch R = 1 ,5340    ,119.7,119.6,119.7
XS GIS Cut Line= 2
1649642.60958437 473957.00563527 1649229.1752277473988.418539821
#Sta/Elev= 30
       0 1120.23    10.9 1114.14      24 1104.95      47 1093.06    50.3 1091.65
    66.8 1087.92    86.8 1079.53    99.7 1075.21   106.3 1071.94   145.8 1047.82
   155.6 1038.76   158.9  1036.5  181.071017.502   181.9 1016.89   188.5 1016.36
   198.4 1016.79  200.01  1017.5     205 1019.35   221.4 1021.12   264.2 1021.28
   280.7 1022.01   293.8 1025.36   310.3 1033.54   321.2 1040.75   359.6 1072.35
   362.9 1074.56   389.2 1091.02     396 1093.65   402.4 1098.16   414.6 1105.22
#Mann= 3 ,-1,0
       0      .1       0  181.07    .045       0  200.01      .1       0
Bank Sta=181.07,200.01
XS Rating Curve= 0 ,0
Exp/Cntr(USF)=0,0
Exp/Cntr=0.3,0.1

Type RM Length L Ch R = 1 ,5221    ,223.9,226.4,227.6
XS GIS Cut Line= 2
1649632.54723995473839.6994054911649196.81985424473868.973079984
#Sta/Elev= 30
       0  1112.3    10.6 1104.18    13.9 1102.22    27.1 1096.78    43.5 1087.54
    50.1  1084.8    63.2 1077.86    89.5 1071.09   102.7 1065.02   112.6 1059.06
   122.4 1051.24   135.6 1043.63   148.7 1033.08     152 1030.98   158.6 1027.65
   168.5 1024.21  188.86 1015.89   194.8 1014.99  204.81 1015.89   260.5 1018.03
   296.7  1017.9   306.6 1019.19   309.9 1020.91   336.2  1040.1   355.9 1057.47
   382.2 1074.29   400.8 1089.52   411.8 1097.15   421.7 1101.41   436.7 1110.77
#Mann= 3 ,-1,0
       0      .1       0  188.86    .045       0  204.81      .1       0
#XS Ineff= 2 , 0
                          273.88         1037.92
Permanent Ineff=
       F       F
Bank Sta=188.86,204.81
XS Rating Curve= 0 ,0
Exp/Cntr(USF)=0,0
Exp/Cntr=0.3,0.1

Type RM Length L Ch R = 1 ,4994    ,209.8,210.8,210.9
XS GIS Cut Line= 2
1649620.56805975473667.3694138891649206.33724115473613.318207141
#Sta/Elev= 30
       0 1098.96    25.1 1086.55    44.9 1080.66    48.2 1079.18    68.1 1069.49
    81.3 1061.21    91.3 1056.88   101.2 1051.19   114.7  1045.4     121 1041.47
   144.2 1024.28     164 1014.05     174 1012.58   207.1 1012.78     213 1010.46
   217.2 1009.32   231.8 1010.47   240.1 1010.75   263.3 1013.25   292.9 1019.36
   306.3 1024.92   311.9 1028.17   319.6  1034.1   332.8 1045.33   345.9 1057.33
   355.9 1064.78   379.1 1080.52   391.8 1087.26   408.9 1097.76   417.7 1104.27
#Mann= 3 ,0,0
       0      .1       0     213    .045       0   231.8      .1       0
Bank Sta=213,231.8
XS Rating Curve= 0 ,0
Exp/Cntr(USF)=0,0
Exp/Cntr=0.3,0.1

Type RM Length L Ch R = 1 ,4784    ,32.8,32.6,33.2
XS GIS Cut Line= 6
1649633.80034444473476.2485444061649548.19782535473458.114722412
1649474.92697452473442.0996625831649376.80807627473422.692877244
1649301.75343635473414.8447958191649214.09941218473406.098750319
#Sta/Elev= 30
       0 1102.53    28.9 1089.02    38.7 1085.65    52.4 1082.07    65.8 1075.43
    89.3 1057.63   122.8 1029.48   136.3  1020.5     143 1018.37   183.2 1013.59
   196.6 1008.14  207.671007.128   213.3 1006.09  220.981007.128   226.7 1008.87
   240.1 1009.93   253.4  1012.4   279.9 1014.25   293.1 1016.75   309.6 1022.35
   319.5 1028.03   342.6 1045.81   355.8 1051.68   362.4 1055.43   382.2 1070.01
   395.4 1076.68   405.3 1084.06   410.1 1086.98   417.7 1090.75   426.1 1093.79
#Mann= 3 ,-1,0
       0      .1       0  207.67    .045       0  220.98      .1       0
Bank Sta=207.67,220.98
XS Rating Curve= 0 ,0
Exp/Cntr(USF)=0,0
Exp/Cntr=0.3,0.1

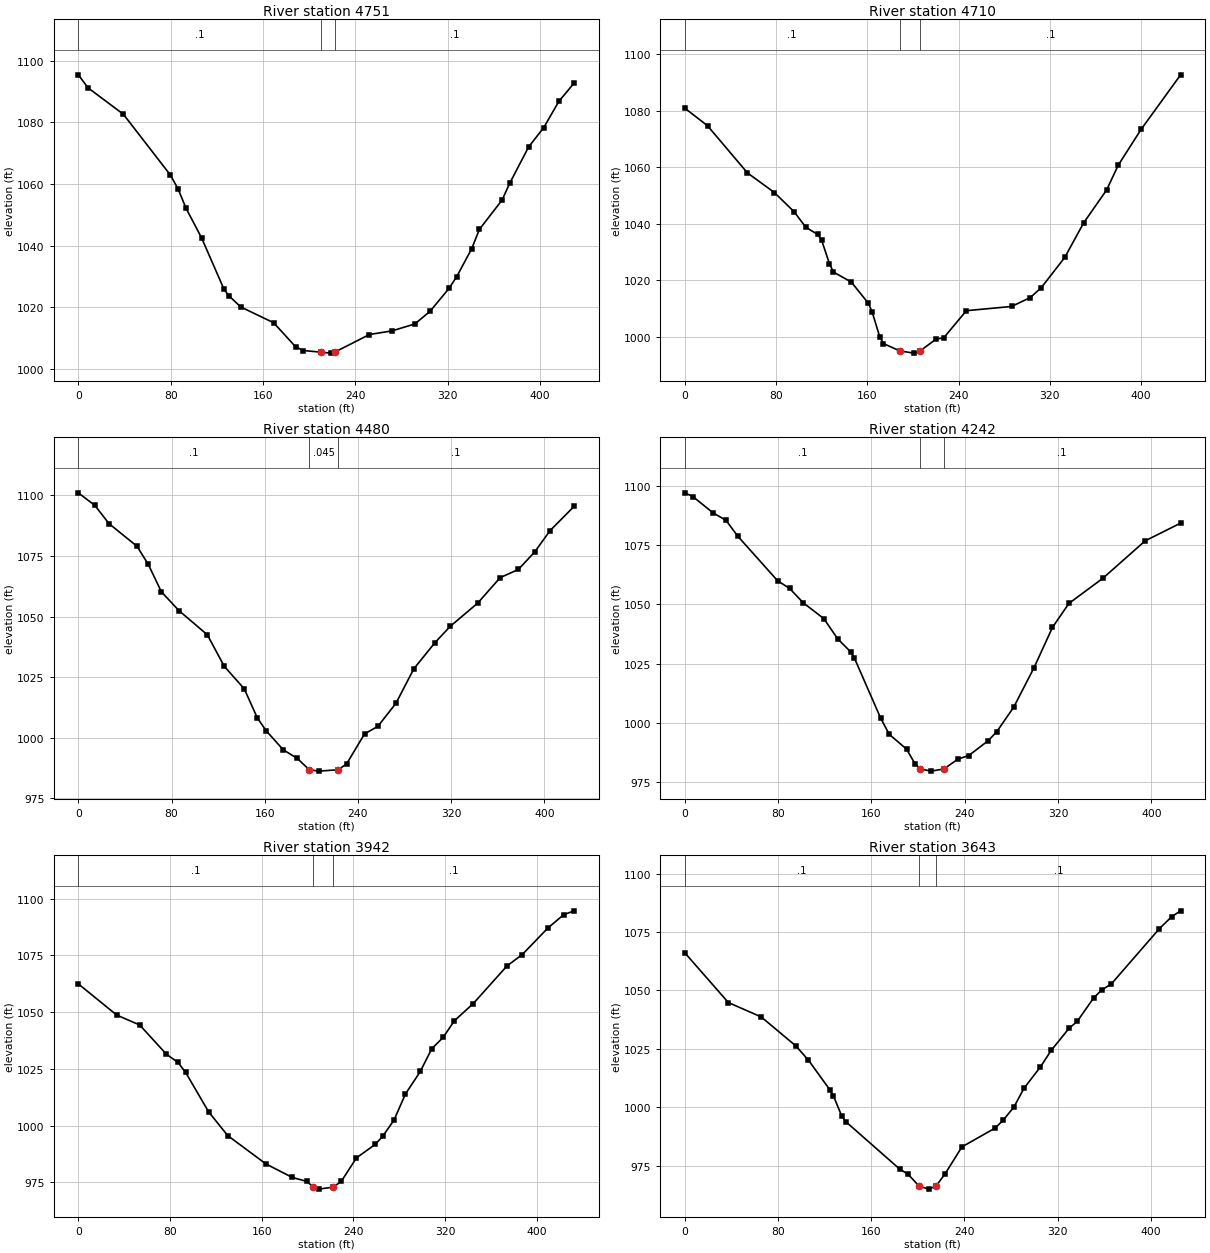
Type RM Length L Ch R = 1 ,4751    ,45.1,41.2,41.1
XS GIS Cut Line= 4
1649636.67483886473453.661497924 1649468.1182262473409.502896523
1649401.34180457473392.8087911151649215.01404744473391.193232527
#Sta/Elev= 30
       0 1095.49     8.4 1091.27      39 1082.68    79.7 1062.94    86.5  1058.3
    93.2 1052.19   106.8 1042.44   126.2 1025.77   130.5 1023.63   140.7 1020.04
   169.2  1014.9   188.2 1007.08   194.9 1005.89  210.16 1005.35   218.6 1005.04
     222 1005.35   252.1 1011.09   271.8 1012.28   291.5 1014.54   304.6 1018.63
     321 1026.07   327.6 1029.83   340.7    1039   347.3 1045.24     367 1054.81
   373.5 1060.18   389.9 1072.02   403.1 1078.37   416.2 1086.89   429.4 1092.83
#Mann= 3 ,-1,0
       0      .1       0  210.16    .045       0     222      .1       0
Bank Sta=210.16,222
XS Rating Curve= 0 ,0
Exp/Cntr(USF)=0,0
Exp/Cntr=0.3,0.1

Type RM Length L Ch R = 1 ,4710    ,236.9,229.5,224.6
XS GIS Cut Line= 4
1649637.54298686473413.8663823811649494.66493713473367.253685305
1649338.61373387473349.0139342751649213.97543517473374.346921817
#Sta/Elev= 30
       0 1080.91    19.9 1074.69    54.9    1058    78.5 1051.06    95.8 1044.25
   106.1 1038.75   116.5 1036.21   119.9 1034.22   126.8 1025.85   130.3 1022.91
     146 1019.35   160.9 1011.86   164.2 1008.81   170.8 1000.08   174.1  997.61
  188.25995.0391   200.5  994.22  206.37995.0388   220.3  999.19   226.9  999.61
   246.8 1009.24   286.4 1010.73   302.9  1013.9   312.5 1017.41     333 1028.06
   349.7 1040.37   369.8    1052   379.9 1060.72   399.9 1073.36   434.6  1092.7
#Mann= 3 ,-1,0
       0      .1       0  188.25    .045       0  206.37      .1       0
Bank Sta=188.25,206.37
XS Rating Curve= 0 ,0
Exp/Cntr(USF)=0,0
Exp/Cntr=0.3,0.1

Type RM Length L Ch R = 1 ,4480    ,236.7,238.1,238.9
XS GIS Cut Line= 6
1649536.68179438473052.3149474211649459.84106879473094.869652325
1649393.90353662473130.9509449991649308.46801196473182.958386907
 1649245.1935322 473223.224054421649171.37281371473270.200010324
#Sta/Elev= 30
       0 1101.07    14.2 1095.86    26.3 1088.38    50.4    1079      60 1071.58
    71.3 1060.22    86.3 1052.51   110.7 1042.52   125.2 1029.53   142.4 1020.22
   153.6 1008.23   161.1 1002.99   175.8   995.1   187.9  991.52  198.16986.8419
   206.4  986.28  222.88986.8416   230.2  989.23   245.6 1001.63   257.1 1004.77
   272.6 1014.29   287.9 1028.48     306 1039.25   319.2 1046.03   342.6 1055.52
     362 1066.09   377.6 1069.46   391.6 1076.66   404.8 1085.47   425.5 1095.51
#Mann= 3 ,-1,0
       0      .1       0  198.16    .045       0  222.88      .1       0
Bank Sta=198.16,222.88
XS Rating Curve= 0 ,0
Exp/Cntr(USF)=0,0
Exp/Cntr=0.3,0.1

Type RM Length L Ch R = 1 ,4242    ,294.3,300,302
XS GIS Cut Line= 6
1649450.00346135472840.9460200821649372.07579568472880.739575669
1649305.28065367472914.8484313341649216.22046433472960.326686844
1649148.73208226472993.0772775111649069.53932726473030.393475845
#Sta/Elev= 30
       0 1097.04       7 1095.43    24.3 1088.57    35.3 1085.48    45.3 1078.84
    79.5 1060.03    89.9 1056.73   101.6 1050.68   119.2 1044.04   131.1  1035.5
   142.2 1030.04   145.4 1027.42     168 1002.03   175.3  995.27   190.1  989.05
   197.4  982.87  201.87 980.689   211.2  979.78   222.1980.6881   234.3  984.88
   243.5  986.35     260  992.56   267.4  996.35     282 1006.73   299.3 1023.25
   315.2 1040.31   329.3 1050.44   358.4 1061.02   394.7 1076.81   425.1 1084.28
#Mann= 3 ,-1,0
       0      .1       0  201.87    .045       0   222.1      .1       0
Bank Sta=201.87,222.1
XS Rating Curve= 0 ,0
Exp/Cntr(USF)=0,0
Exp/Cntr=0.3,0.1

Type RM Length L Ch R = 1 ,3942    ,291.3,299.1,300
XS GIS Cut Line= 6
  1649385.825112472684.5329470931649294.31774908472667.187837422
1649218.66107626472653.701643929 1649118.8476276472659.811867923
1649043.98786917472664.3955201661648956.65142967472669.742294252
#Sta/Elev= 30
       0 1062.45    33.5  1048.7    53.5 1044.34    76.9 1031.41    86.9 1027.86
    93.6 1023.42   113.6 1006.09   130.3  995.57   163.6  983.09   186.7   977.1
   199.2  975.39  205.11972.8542   209.7  971.97  222.29 972.855   229.4  975.39
   242.6  985.75     259   991.7   265.6  995.33   275.4 1002.44   285.3 1013.88
   298.3 1023.85   308.3 1033.88   318.2 1038.84     328 1046.19   344.5 1053.78
     374 1070.41   387.2 1075.37   409.8 1087.18   423.3 1092.93   432.5 1094.66
#Mann= 3 ,-1,0
       0      .1       0  205.11    .045       0  222.29      .1       0
Bank Sta=205.11,222.29
XS Rating Curve= 0 ,0
Exp/Cntr(USF)=0,0
Exp/Cntr=0.3,0.1

Type RM Length L Ch R = 1 ,3643    ,304.3,300.9,299.7
XS GIS Cut Line= 6
1649457.90009908472453.017333999 1649372.9530905472430.308061838
1649303.82626025472401.2100229261649211.73326859472362.197633758
1649141.93517984472334.5776102541649060.44977851472302.475968421
#Sta/Elev= 30
       0 1066.13    37.4 1044.82    65.6 1038.66    95.4 1026.21   106.1 1020.16
   124.7 1007.32   127.5 1004.93   134.6  996.34   138.1  993.84   184.4  973.51
   191.6  971.31  201.11966.1852   209.4   964.9  215.67966.1833   223.6  971.59
   237.9     983   266.4  991.06   273.4  994.49   282.6 1000.14   291.1 1008.07
   305.2 1017.19   314.6 1024.39   329.9 1033.82   336.9 1036.78     351 1046.84
   358.1  1050.3     366 1052.71   407.4 1076.49     418 1081.63   425.6 1084.11
#Mann= 3 ,-1,0
       0      .1       0  201.11    .045       0  215.67      .1       0
Bank Sta=201.11,215.67
XS Rating Curve= 0 ,0
Exp/Cntr(USF)=0,0
Exp/Cntr=0.3,0.1

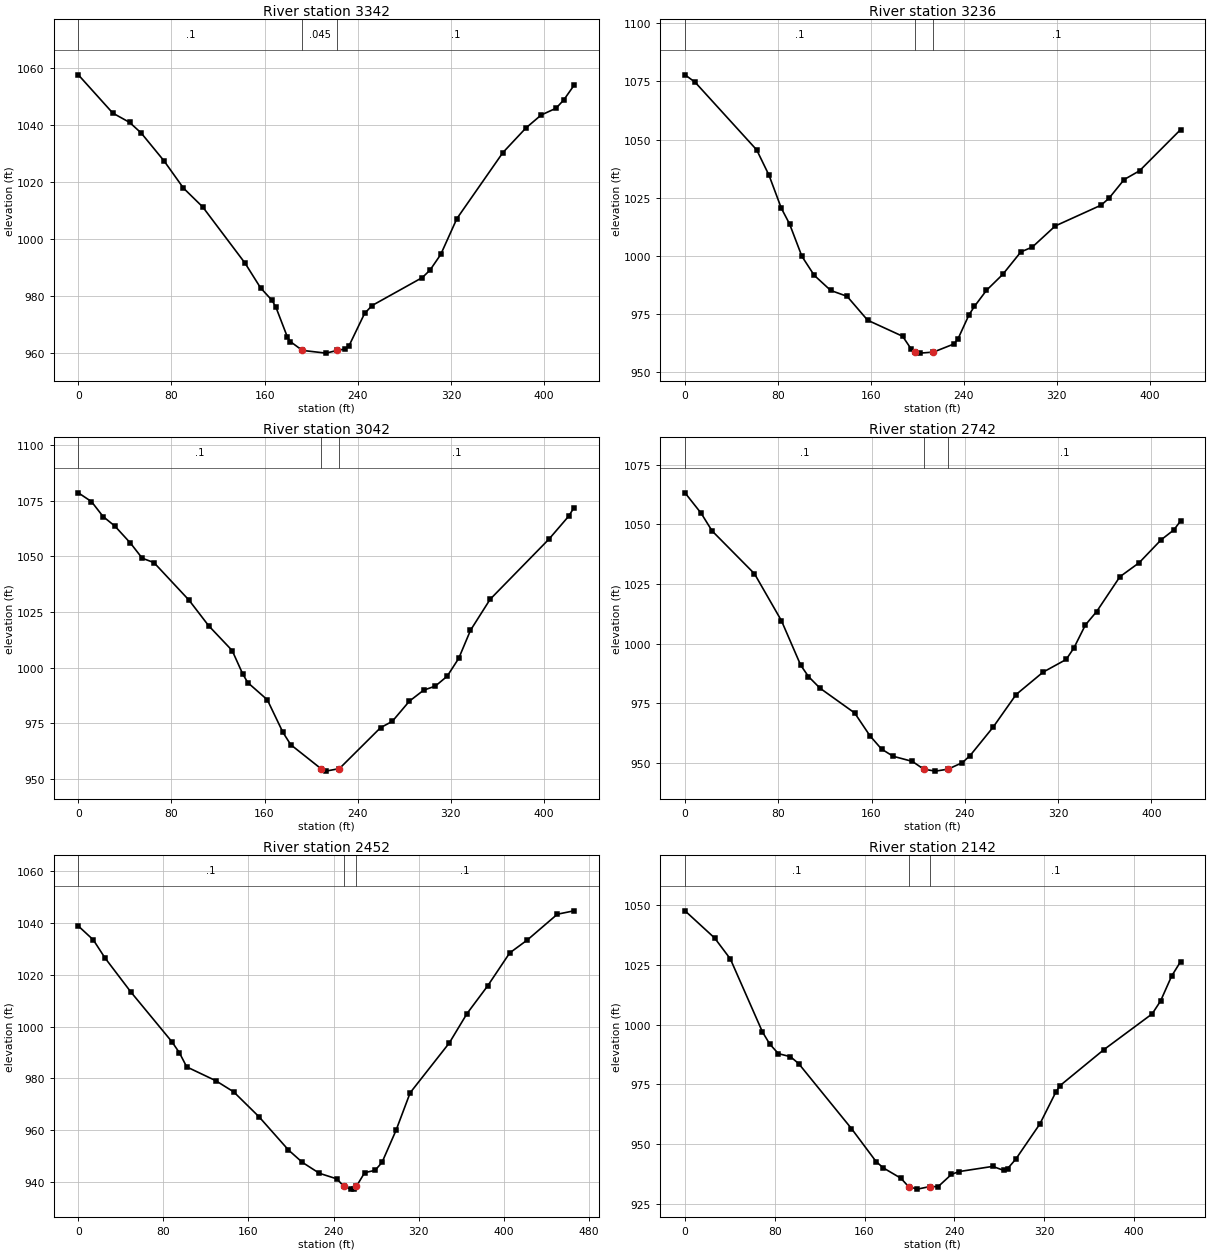
Type RM Length L Ch R = 1 ,3342    ,111.8,106.3,100.9
XS GIS Cut Line= 6
1649524.52266926472116.0921548461649437.72756726472105.010484084
1649363.33106251472095.513127759  1649264.136379472082.850095332
1649189.74020234472073.3520828341649101.68033908472073.857331172
#Sta/Elev= 30
       0 1057.54    29.6 1044.11      44 1040.85    53.9 1037.16    73.6 1027.34
    90.3 1017.77   106.8 1011.18   143.2  991.43   156.5  982.77   166.4  978.36
   169.7  975.96   179.6  965.44   182.1  963.91  192.36960.8293   212.7  959.87
  222.34960.8289   229.2  961.34   232.5  962.48   245.8  973.78   252.2  976.56
   295.4  986.39     302     989   311.2  994.49   325.1  1007.1   364.6 1030.26
   384.3 1038.86   397.4 1043.42   410.2 1045.81   416.8 1048.69   425.6 1053.82
#Mann= 3 ,-1,0
       0      .1       0  192.36    .045       0  222.34      .1       0
Bank Sta=192.36,222.34
XS Rating Curve= 0 ,0
Exp/Cntr(USF)=0,0
Exp/Cntr=0.3,0.1

Type RM Length L Ch R = 1 ,3236    ,192.6,193.7,194.9
XS GIS Cut Line= 3
1649498.76138701471910.7516795651649261.70184549 472006.08167313
1649091.28893664 472021.26698184
#Sta/Elev= 30
       0 1077.84     8.7 1074.66    61.7 1045.58    72.3 1034.69    82.9 1020.52
      90 1013.76   100.6  999.86   111.2   991.7   125.4  985.19   139.5  982.66
   157.2  972.39   187.3   965.5   194.8  959.91  198.26  958.68   202.4  958.25
   213.8  958.69   231.5  962.19     235  964.41   244.5  974.77   249.1  978.31
   259.5  985.25   273.5  992.09   289.1 1001.75     299 1003.84   318.7  1012.9
   358.2 1021.85   364.9 1024.78     378 1032.85   391.2 1036.59   426.6 1054.31
#Mann= 3 ,-1,0
       0      .1       0  198.26    .045       0   213.8      .1       0
Bank Sta=198.26,213.8
XS Rating Curve= 0 ,0
Exp/Cntr(USF)=0,0
Exp/Cntr=0.3,0.1

Type RM Length L Ch R = 1 ,3042    ,298.9,300,301.2
XS GIS Cut Line= 6
1649475.45977525471756.2221396711649389.98127167471774.921249256
1649316.71370168471790.9491043391649219.02360834471812.318812251
1649145.44829617471828.4024415021649059.72832325471848.786915168
#Sta/Elev= 30
       0 1078.66    11.3 1074.71    21.3 1067.97    31.4 1063.69    44.8 1056.02
    54.9 1049.22      65 1047.23    95.2 1030.28     112 1018.81   132.2 1007.64
   141.2  997.18   145.6  993.21   162.4  985.47   175.8  970.82   182.5  965.26
  208.42954.4886   212.8  953.34  224.36954.4862   259.7   972.9   269.8  975.75
   284.5  984.85   296.7  989.78   306.8  991.64   316.9  996.04   326.9 1004.13
     337 1016.76   353.9 1030.74   404.5 1057.85   421.3 1068.09   425.9 1071.93
#Mann= 3 ,-1,0
       0      .1       0  208.42    .045       0  224.36      .1       0
Bank Sta=208.42,224.36
XS Rating Curve= 0 ,0
Exp/Cntr(USF)=0,0
Exp/Cntr=0.3,0.1

Type RM Length L Ch R = 1 ,2742    ,290,290,290.3
XS GIS Cut Line= 6
1649408.76174593471487.8972170051649321.87149976471498.726919755
1649247.37525767471507.5077420921649147.87151967 471517.45686917
1649073.24371618471524.9191245881648986.17794542471533.625143915
#Sta/Elev= 30
       0 1063.26    13.9 1054.66    23.2 1047.31    59.6 1029.33    82.7 1009.67
    99.2  991.05   105.9  986.26   115.8  981.38   145.5     971   158.7  961.38
   168.6  955.85   178.5  952.85     195   950.7  204.75947.4313   214.8  946.62
  225.49 947.432   237.8  950.15   244.4  953.07   264.2     965     284  978.73
   307.1   988.1   326.9  993.41   333.5  998.19   343.4 1007.87   353.1 1013.52
     373 1028.09   389.5 1033.95   408.4 1043.59   419.2 1047.68   425.1 1051.49
#Mann= 3 ,-1,0
       0      .1       0  204.75    .045       0  225.49      .1       0
Bank Sta=204.75,225.49
XS Rating Curve= 0 ,0
Exp/Cntr(USF)=0,0
Exp/Cntr=0.3,0.1

Type RM Length L Ch R = 1 ,2452    ,310.4,310,312.8
XS GIS Cut Line= 6
1649386.31592467471291.1384241731649286.40864417471254.570583925
1649197.79267967471231.5141995851649092.19938692471231.031589001
1649018.59487534471245.4321507511648932.72299984471262.232970178
#Sta/Elev= 30
       0 1038.87    14.1 1033.51    25.1 1026.52    49.5 1013.32      88  994.14
      95  989.92   101.9  984.43   129.2   979.1   146.1  974.77   169.9  965.15
   197.6   952.3   210.6  947.55   226.6  943.32     243  941.16  249.68938.2731
   256.1  937.19   259.4  937.29  261.48938.2715   269.2  943.55     279  944.45
   285.5  947.49   298.7  959.89     312  974.43   348.8  993.68   365.5 1005.06
   384.8 1015.69   405.6 1028.47   422.2 1033.48   450.4 1043.43     466 1044.74
#Mann= 3 ,-1,0
       0      .1       0  249.68    .045       0  261.48      .1       0
Bank Sta=249.68,261.48
XS Rating Curve= 0 ,0
Exp/Cntr(USF)=0,0
Exp/Cntr=0.3,0.1

Type RM Length L Ch R = 1 ,2142    ,169.3,162.6,159.1
XS GIS Cut Line= 6
1649538.05249783471115.0075428341649456.89813259471081.354723006
1649389.03311084471049.3157450851649300.07626776471003.635390252
1649228.45862883470972.2312535941649136.09628075470932.029562339
#Sta/Elev= 30
       0 1047.61    26.4 1036.24    40.4 1027.49      69  996.97    75.5  991.89
    83.2  987.86      94  986.58   101.3  983.69   148.4  956.49   170.3  942.72
   176.6   940.1   192.4  935.74  199.29  932.21   207.2  931.17   218.3  932.25
   225.6   932.2   237.5  937.33   244.1   938.5   274.3  940.68     284  939.03
   287.6  939.78   294.8  943.68   316.3  958.42   330.6  971.81   334.3  974.48
   373.5  989.57   416.4 1004.49   423.9 1009.87   433.8 1020.33   441.8  1026.4
#Mann= 3 ,0,0
       0      .1       0  199.29    .045       0   218.3      .1       0
Bank Sta=199.29,218.3
XS Rating Curve= 0 ,0
Exp/Cntr(USF)=0,0
Exp/Cntr=0.3,0.1

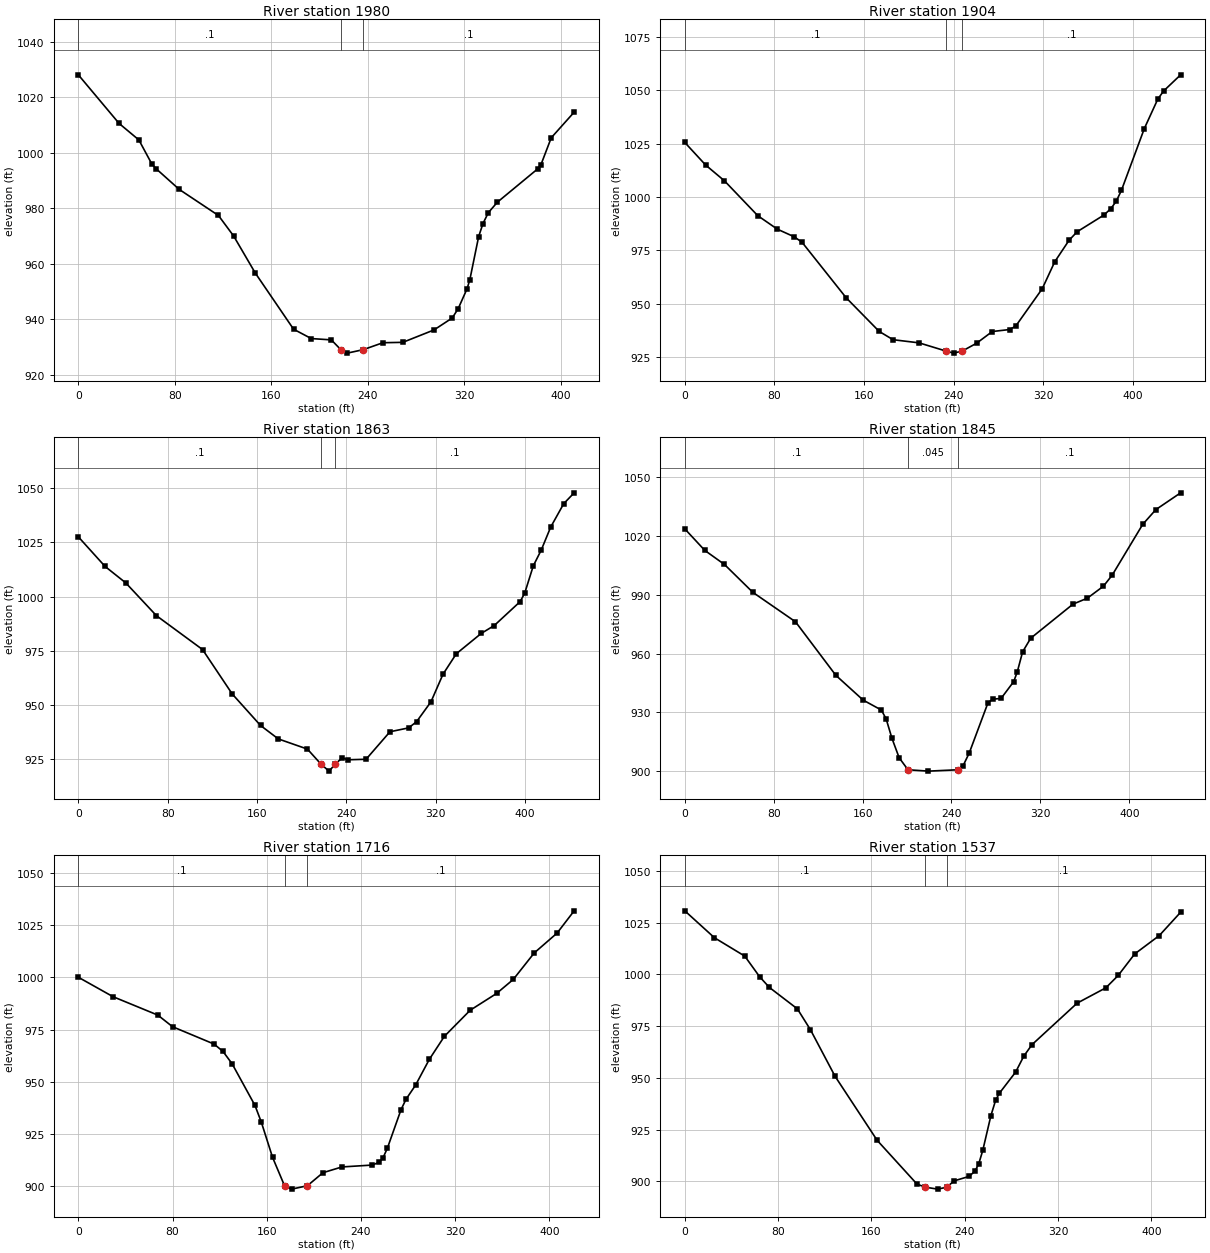
Type RM Length L Ch R = 1 ,1980    ,66.7,75.5,82.2
XS GIS Cut Line= 4
1649556.43744568470947.3046673931649376.93093592470869.518513163
1649277.86993608470876.8317413381649173.49022485 470825.63914411
#Sta/Elev= 30
       0 1028.15    33.8 1010.62    50.2 1004.67    60.9  996.03    64.5  994.29
    83.7  986.82   116.2  977.42   128.8  970.02   146.7   956.7   178.5  936.41
   193.2  933.03   209.8  932.56   217.8928.9867     223  927.78   236.2  929.02
   252.6  931.53   269.1  931.67     295  936.15   310.1  940.46     315   943.8
   322.4  951.01   324.7   954.3     332  969.83   335.6  974.53     340  978.42
   347.5  982.21   381.2  994.32   383.7  995.79   392.2 1005.45   411.2 1014.69
#Mann= 3 ,-1,0
       0      .1       0   217.8    .045       0   236.2      .1       0
Bank Sta=217.8,236.2
XS Rating Curve= 0 ,0
Exp/Cntr(USF)=0,0
Exp/Cntr=0.3,0.1

Type RM Length L Ch R = 1 ,1904    ,39.4,40.8,41.2
XS GIS Cut Line= 4
1649565.94560632470927.9996904171649400.40071399470848.883858338
1649330.59262686470760.460281308 1649246.8229223470640.124435876
#Sta/Elev= 30
       0 1025.51    18.6 1014.95    35.4 1007.56    65.2  991.23    82.6  984.94
    97.9  981.32   104.8  978.74   144.1  952.83   173.6  937.08     186   933.2
   209.2  931.73  233.26927.8895     240  926.92  247.75927.8895   260.6  931.55
   274.6  937.03   290.2  937.97   295.6  939.62   319.2  957.04   330.4  969.69
   343.2  979.76   350.4  983.73   374.4  991.57   380.5  994.55   385.2  997.92
   389.9 1003.03   410.4 1032.04   422.4 1045.78   427.6 1049.59   442.8 1057.16
#Mann= 3 ,-1,0
       0      .1       0  233.26    .045       0  247.75      .1       0
Bank Sta=233.26,247.75
XS Rating Curve= 0 ,0
Exp/Cntr(USF)=0,0
Exp/Cntr=0.3,0.1

Type RM Length L Ch R = 1 ,1863    ,17.8,18.2,37.5
XS GIS Cut Line= 3
1649587.23313173470910.8802688451649421.68823939470822.456691814
1649284.06658191470606.384041174
#Sta/Elev= 30
       0 1027.61    23.9 1013.97    42.5 1006.35    69.9  991.25   111.2  975.62
   137.8  955.12   163.1  940.62     179  934.41   205.1  929.71   217.2  922.81
   224.4  919.55   230.2  922.82   236.3   925.8     241  924.78   257.6  925.02
     279  937.71   295.7  939.49   302.8  942.34   315.7  951.52   326.5  964.26
   338.4  973.68   360.7  983.06   372.4  986.71   395.5  997.71   399.6 1001.58
   407.3 1014.21   414.5 1021.59   422.9 1032.11   434.6 1042.93   443.9  1047.9
#Mann= 3 ,-1,0
       0      .1       0   217.2    .045       0   230.2      .1       0
Bank Sta=217.2,230.2
XS Rating Curve= 0 ,0
Exp/Cntr(USF)=0,0
Exp/Cntr=0.3,0.1

Type RM Length L Ch R = 1 ,1845    ,133.1,129.2,119.9
XS GIS Cut Line= 6
1649582.68987575470904.4902473391649497.43446884470854.731816679
1649429.76006351470803.5399899181649380.01934934470716.775727749
1649341.77041009470652.2620772571649293.36794785470579.236304671
#Sta/Elev= 30
       0 1023.74      18 1012.74    35.7 1005.55    61.2  991.34    99.6  976.29
   135.9  948.95   160.5  936.28   176.9   931.2   181.2  926.66   186.4  916.79
   192.9  906.82  200.85900.6907   219.3     900  245.75900.6929   250.5  902.84
     256  909.29   272.8  934.84     277  936.76   284.6  937.12     296  945.74
   299.2  950.69     304  960.93   311.3  967.89   349.4  985.32   362.2  988.31
   376.7  994.44   384.6 1000.09   412.1 1026.05   423.9 1033.57   446.2 1042.15
#Mann= 3 ,-1,0
       0      .1       0  200.85    .045       0  245.75      .1       0
Bank Sta=200.85,245.75
XS Rating Curve= 0 ,0
Exp/Cntr(USF)=0,0
Exp/Cntr=0.3,0.1

Type RM Length L Ch R = 1 ,1716    ,181,178.9,177
XS GIS Cut Line= 2
1649663.26375358470790.6517189411649307.86220475470564.934799941
#Sta/Elev= 30
       0 1000.12    29.5  990.76    67.5  981.92      80  976.34   115.2  968.01
   122.8  964.48   130.6   958.5     150  938.48   155.4  930.44   164.9  913.57
   175.1899.8747   181.1  898.28   194.5  899.91   207.7  906.17   223.8  908.94
   249.6  909.85   255.7  911.25   258.8  913.46   262.4  917.94     274  936.48
   278.3  941.54   286.3  948.21     298  960.63   310.8  971.71   332.7  984.25
   355.1  992.31   369.3  999.06   387.1  1011.8   406.5 1021.34     421 1032.04
#Mann= 3 ,-1,0
       0      .1       0   175.1    .045       0   194.5      .1       0
Bank Sta=175.1,194.5
XS Rating Curve= 0 ,0
Exp/Cntr(USF)=0,0
Exp/Cntr=0.3,0.1

Type RM Length L Ch R = 1 ,1537    ,301.4,300,299.3
XS GIS Cut Line= 6
1649758.46478668470599.1493225841649676.85340133 470567.59328334
1649606.90045726470540.5451090931649513.62997451470504.480876759
1649443.67735851470477.4327025121649362.06564508470445.876007095
#Sta/Elev= 30
       0 1030.72    25.4 1017.71    51.4 1008.83    64.2  998.82    72.5  993.69
    96.5  983.33   107.7  973.24   128.8  950.74   164.9  919.77   199.1  898.59
  206.29897.1359   216.7   896.2  224.58897.1365   230.8  900.18   243.6  902.34
   248.7  904.86   251.9  908.34   255.4   914.9   262.4  931.77   266.4  939.11
   269.5  942.44   283.6   952.8   290.6  960.51   297.6  966.03   336.3   986.1
   360.9   993.5   371.5  999.49   385.6 1009.86   406.7 1018.76     425 1030.03
#Mann= 3 ,-1,0
       0      .1       0  206.29    .045       0  224.58      .1       0
Bank Sta=206.29,224.58
XS Rating Curve= 0 ,0
Exp/Cntr(USF)=0,0
Exp/Cntr=0.3,0.1

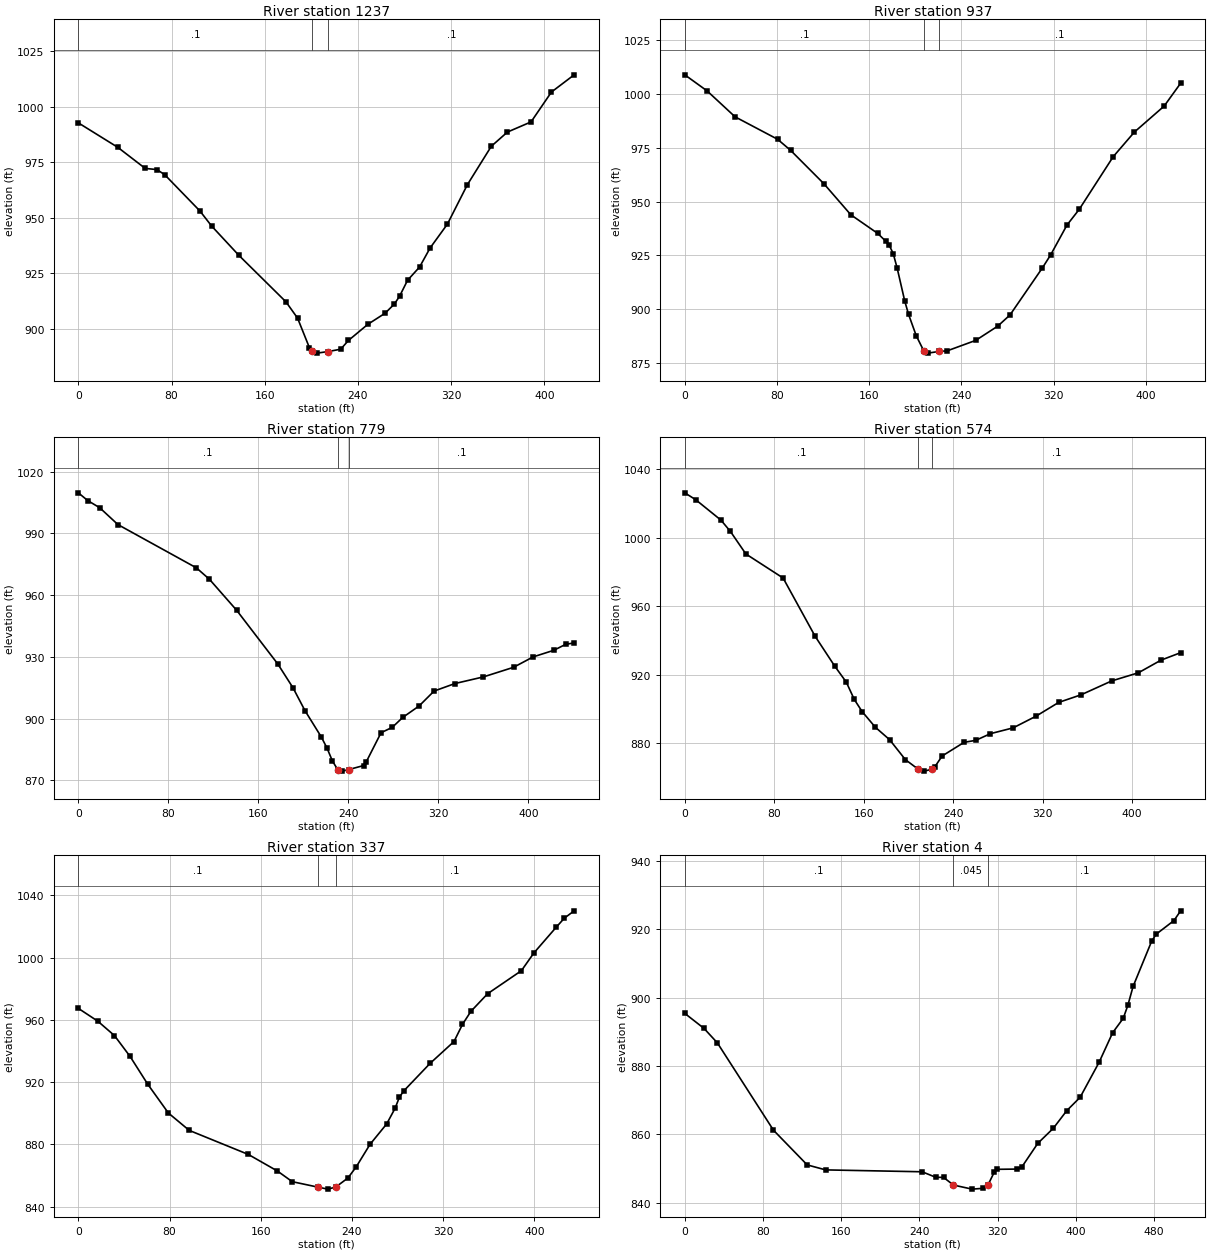
Type RM Length L Ch R = 1 ,1237    ,297.3,300,297.4
XS GIS Cut Line= 6
1649868.35006559470285.5715376731649782.79216585470267.238569096
1649709.45701067470251.5240335911649611.67669442470230.571647674
1649539.55872843470209.1766773461649455.70194076470182.904092088
#Sta/Elev= 30
       0  992.81    33.9  981.78    57.4   972.3    67.5  971.77    74.2  969.44
   104.4  953.11   114.4  946.36   137.9   933.1   178.2  912.23   188.2  904.87
   198.3  891.63   200.9  889.86     205  889.12   214.7  889.85   225.2  890.89
   231.9  894.85   248.6  902.13   263.3  907.08   271.3  911.24   275.7   914.7
   282.6  921.93   292.9  927.88   301.9  936.43   316.8  947.22   333.9  964.93
   354.5  982.28   368.3  988.66   388.6  993.24   406.1 1006.69   425.6 1014.44
#Mann= 3 ,0,0
       0      .1       0   200.9    .045       0   214.7      .1       0
Bank Sta=200.9,214.7
XS Rating Curve= 0 ,0
Exp/Cntr(USF)=0,0
Exp/Cntr=0.3,0.1

Type RM Length L Ch R = 1 ,937     ,157.9,161.7,164.1
XS GIS Cut Line= 6
1650002.63030884470026.7078821661649916.87687142470009.299780503
1649843.26514201469994.9362921711649745.11606009469975.785411835
 1649674.2008476469947.6010850071649592.76990809469906.431547925
#Sta/Elev= 30
       0 1008.82    19.4 1001.34    43.6  989.34    80.5  978.92    91.8  973.77
   120.6  958.33     144   943.9   167.4  935.22   174.1  931.73   177.4  929.66
   180.8  925.88   184.2  919.17   190.8  903.84   194.1  897.68   200.8  887.72
   207.5  880.54   210.8   879.7   220.9   880.5   227.5  880.74   252.4  885.62
   271.5  892.24   282.1  897.41   310.2  919.25   317.4  925.31   331.5  939.11
   342.2  946.45   371.6  970.83     390  982.27   415.8  994.31   430.1 1004.91
#Mann= 3 ,0,0
       0      .1       0   207.5    .045       0   220.9      .1       0
Bank Sta=207.5,220.9
XS Rating Curve= 0 ,0
Exp/Cntr(USF)=0,0
Exp/Cntr=0.3,0.1

Type RM Length L Ch R = 1 ,779     ,207,200.4,198.4
XS GIS Cut Line= 2
1650004.92231506470018.5525426881649705.43428218469695.442918481
#Sta/Elev= 30
       0 1009.75     8.4 1005.97      19  1002.5    35.2  994.31   104.9  973.29
   116.5  967.73   140.7  952.65   177.3  926.52   190.8  914.95   201.4  903.88
   215.9  891.09     221  885.67   225.7  879.52   230.4  875.26   234.6  874.48
   240.4875.2584   253.5  877.19   255.8  878.94     269  893.14     279  895.78
   288.3  900.59   302.8  906.15   316.1  913.39   334.7  917.06   359.9  920.27
   386.7  924.93   404.1  929.99   422.5  933.21   433.1  936.12   440.6   936.8
#Mann= 3 ,-1,0
       0      .1       0   230.4    .045       0   240.4      .1       0
Bank Sta=230.4,240.4
XS Rating Curve= 0 ,0
Exp/Cntr(USF)=0,0
Exp/Cntr=0.3,0.1

Type RM Length L Ch R = 1 ,574     ,230.4,237.5,238.5
XS GIS Cut Line= 4
1650144.05067604469800.5320813581649987.88720847469694.227248699
1649921.14848321469693.7910478811649739.55307908469646.691581845
#Sta/Elev= 30
       0 1026.19     9.8 1022.14    32.3 1010.25    40.8 1003.61    54.6  990.46
    87.9  976.39   116.5  942.36     134  924.95   144.4  915.53   151.5  905.46
   158.5  898.38   170.3  889.21   183.1  881.91   197.2  870.26  208.85864.5536
   213.7  863.53  220.99864.5521   223.5  866.02   230.1  872.38   249.7  880.36
   260.1  881.52   273.3  885.43   293.6  888.82     314  895.64   334.3   903.7
   354.3  908.14   381.7  916.26   405.5     921   425.8  928.41   443.3  932.76
#Mann= 3 ,-1,0
       0      .1       0  208.85    .045       0  220.99      .1       0
Bank Sta=208.85,220.99
XS Rating Curve= 0 ,0
Exp/Cntr(USF)=0,0
Exp/Cntr=0.3,0.1

Type RM Length L Ch R = 1 ,337     ,354.7,332.5,313.5
XS GIS Cut Line= 6
 1650188.4829555469564.4305915091650104.59992117469523.806657001
1650033.91338275 469487.85298875 1649945.0152666469442.058460921
1649878.34217159469407.711744845  1649800.556566469367.640630752
#Sta/Elev= 30
       0  967.35    17.1  959.11    31.7  949.87    45.4  936.48    60.8  918.75
      79  900.16    97.3  889.01   149.2  873.55   174.6  862.95   187.7  856.08
  209.91 852.628   218.9   851.3  225.82852.6288   236.5  858.44   243.8   865.6
   255.9  880.04   270.5  893.14   277.9  903.21   281.6  910.18   285.3  914.19
   308.6  932.03   329.6  946.07     337  957.04   344.4  965.42   359.1  976.76
   388.7  991.53   399.7 1002.95   419.1 1019.31   426.4 1025.26     435 1029.97
#Mann= 3 ,-1,0
       0      .1       0  209.91    .045       0  225.82      .1       0
Bank Sta=209.91,225.82
XS Rating Curve= 0 ,0
Exp/Cntr(USF)=0,0
Exp/Cntr=0.3,0.1

Type RM Length L Ch R = 1 ,4       ,5737.7,5737.7,5737.7
XS GIS Cut Line= 6
1650199.82906142468921.958123177 1650155.9948315469082.398091003
1650108.27937576469144.6348431711650038.64762525469216.407993585
 1649986.4243045469270.2385945921649925.49693292469333.040962428
#Sta/Elev= 30
       0  895.37    19.7  890.97    33.3  886.76    90.7  861.24   125.2   851.1
   144.1  849.64   242.8  849.09   256.7  847.48   264.7  847.45  274.79  845.21
   293.9  844.02   305.5  844.26  310.12  845.21   316.5  848.95   319.4  849.81
   340.1  849.88   344.9  850.55   361.1   857.4     377  861.81   390.7  866.94
   404.4  870.85   423.8  881.08   437.7  889.74   448.5  893.93   453.2  897.71
   458.6  903.27   477.5  916.42   482.1  918.49   500.4   922.5   507.2  925.34
#Mann= 3 ,-1,0
       0      .1       0  274.79    .045       0  310.12      .1       0
Bank Sta=274.79,310.12
XS Rating Curve= 0 ,0
Exp/Cntr=0.3,0.1
LCMann Table=0

Chan Stop Cuts=-1
Use User Specified Reach Order=0
Composite Channel Slope=5